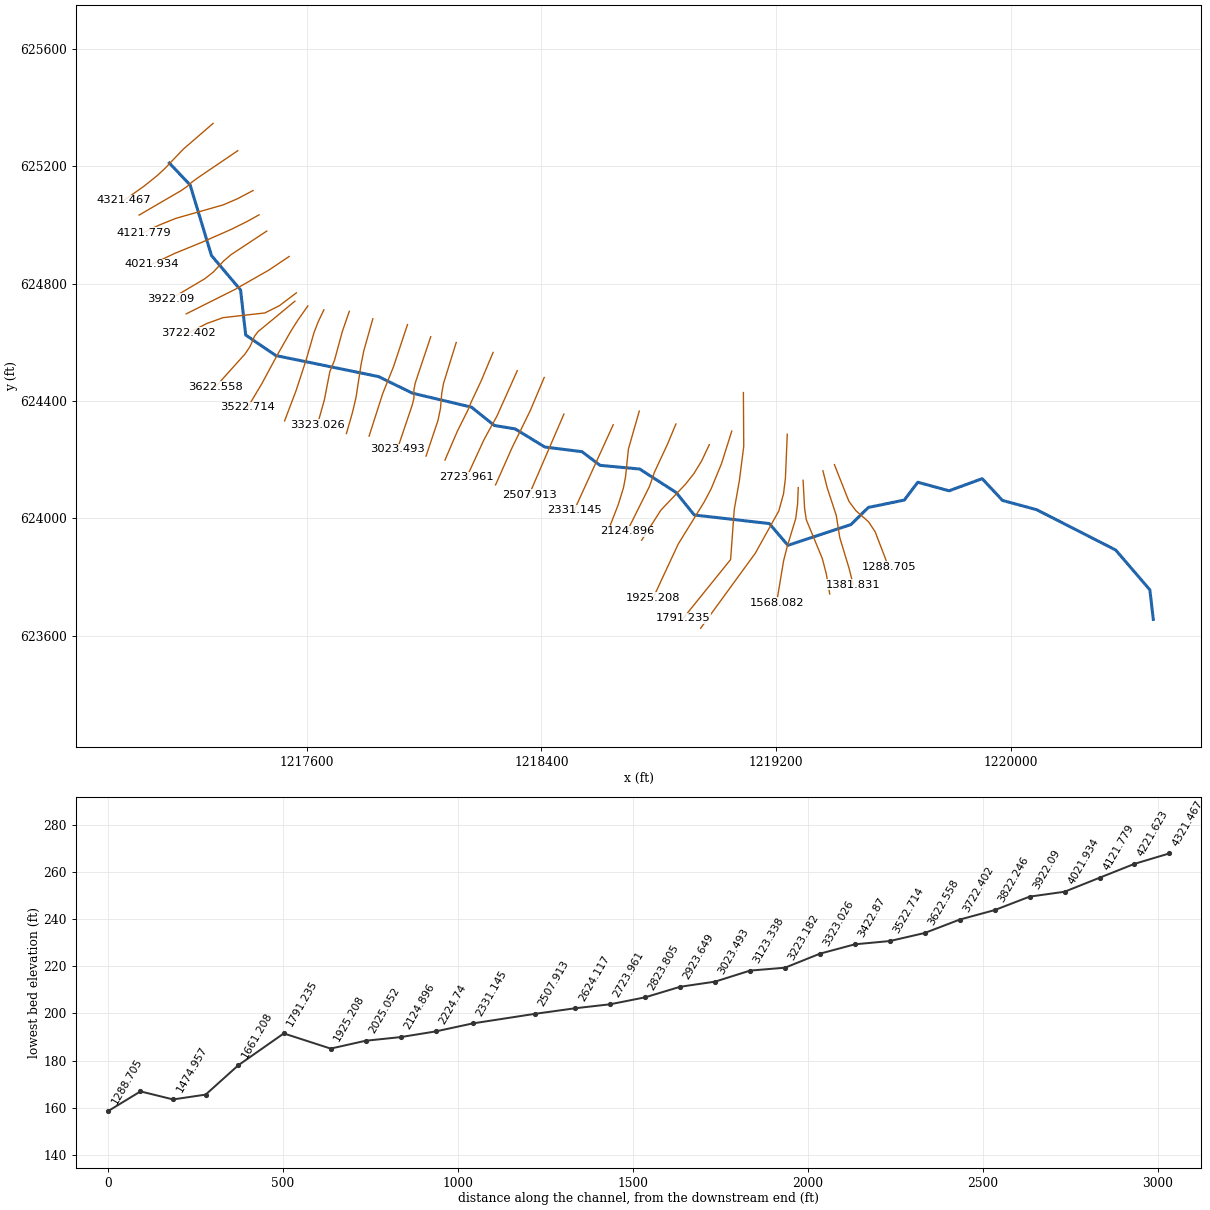
--- 222_ras.prj (project) ---

Proj Title=222
Current Plan=p01
Default Exp/Contr=0.3,0.1
English Units
Geom File=g01
Flow File=f01
Plan File=p01
Y Axis Title=Elevation
X Axis Title(PF)=Main Channel Distance
X Axis Title(XS)=Station
BEGIN DESCRIPTION:
RFD model 222 exported to HEC-RAS
END DESCRIPTION:

--- 222_ras.p01 (plan) ---

Plan Title=Plan 01
Program Version=4.10
Short Identifier=Plan 01
Geom File=g01
Flow File=f01
Subcritical Flow
Calc Critical at every XS
Secant Critical Depth

--- 222_ras.f01 (steady flow) ---

Flow Title=Flow 01
Program Version=5.01
Number of Profiles= 5
Profile Names=10yr,25yr,50yr,100yr,500yr
River Rch & RM=222,39,4321.467
  364.17  431.09  513.04  542.97  630.37
River Rch & RM=222,39,3522.714
   392.2  469.34  559.93  599.14  705.44
River Rch & RM=222,39, 3422.87
   395.6     474  565.66  606.04  714.74
River Rch & RM=222,39,3323.026
  404.73  486.55  581.08  624.66  739.89
River Rch & RM=222,39,3223.182
  416.68  503.06  601.37  649.28   773.3
River Rch & RM=222,39,3123.338
  421.32  509.49  609.28  658.89   786.4
River Rch & RM=222,39,3023.493
   451.8  551.95  661.59  722.89   874.3
River Rch & RM=222,39,2923.649
  457.94  560.55   672.2  735.95  892.38
River Rch & RM=222,39,2823.805
  461.96   566.2  679.17  744.54  904.29
River Rch & RM=222,39,2723.961
  465.27  570.85  684.91  751.63  914.13
River Rch & RM=222,39,2624.117
  467.89  574.54  689.46  757.25  921.96
River Rch & RM=222,39,2507.913
  529.43  661.95  797.62  892.21 1112.03
River Rch & RM=222,39,2331.145
  536.91  672.68  810.93  908.98 1135.95
River Rch & RM=222,39, 2224.74
  540.59  677.97  817.49  917.26 1147.79
River Rch & RM=222,39,2124.896
  542.68  680.97  821.21  921.96 1154.52
River Rch & RM=222,39,2025.052
  545.27  684.69  825.84   927.8 1162.89
River Rch & RM=222,39,1925.208
  550.39  692.08     835   939.4 1179.51
River Rch & RM=222,39,1791.235
  551.91  694.27  837.73  942.85 1184.46
River Rch & RM=222,39,1661.208
  555.95  700.09  844.95     952 1197.61
River Rch & RM=222,39,1568.082
  558.94  704.41  850.32  958.81 1207.41
River Rch & RM=222,39,1474.957
   562.4  709.41  856.53   966.7 1218.78
River Rch & RM=222,39,1381.831
  564.86  712.96  860.94   972.3 1226.85
River Rch & RM=222,39,1288.705
  569.71     720  869.68  983.42 1242.89
River Rch & RM=222,39,1102.454
  574.99  727.64  879.18  995.52 1260.38
River Rch & RM=222,39,916.2027
   578.3  732.45  885.16 1003.15 1271.43
River Rch & RM=222,39,729.9514
  580.65  735.86  889.41 1008.56 1279.28
Boundary for River Rch & Prof#=222,39,1
Up Type= 0
Dn Type= 2
Boundary for River Rch & Prof#=222,39,2
Up Type= 0
Dn Type= 2
Boundary for River Rch & Prof#=222,39,2
Up Type= 0
Dn Type= 2
Boundary for River Rch & Prof#=222,39,2
Up Type= 0
Dn Type= 2
Boundary for River Rch & Prof#=222,39,2
Up Type= 0
Dn Type= 2

--- 222_ras.g01 (geometry) ---

Geom Title=222
Program Version=4.10

River Reach=222,39
Reach XY= 30
1217132.36402472625210.4539833531217203.19733498625135.454003542
1217275.69730668624895.454072677 1217374.8639407624777.954104719
1217392.36393109 624624.620816381217494.86389881624554.620834185
1217844.86379346624482.9541786491217960.69709098624426.287525475
1218161.53036366624378.7875337551218239.86367207624316.287550054
1218310.69698417624304.6208847931218411.53028595 624242.95423351
 1218538.1969148624227.1209012211218599.86356192624180.454246632
1218734.86352171624167.9542463961218859.03014943624087.954266572
1218920.69679568624011.2876208841219176.53005265623982.120955457
1219239.86336516623907.9543090031219454.86330378623978.787615068
1219514.02995466624037.1209293531219636.52991932624062.120918413
1219682.36324081624122.9542323521219789.02987516624093.787571246
1219901.79243053624135.1135387861219970.95907469624060.946892147
1220087.62570594624029.2802314991220356.52970192623892.120948017
1220473.19633023 623756.287651621220484.86299052623655.454347858

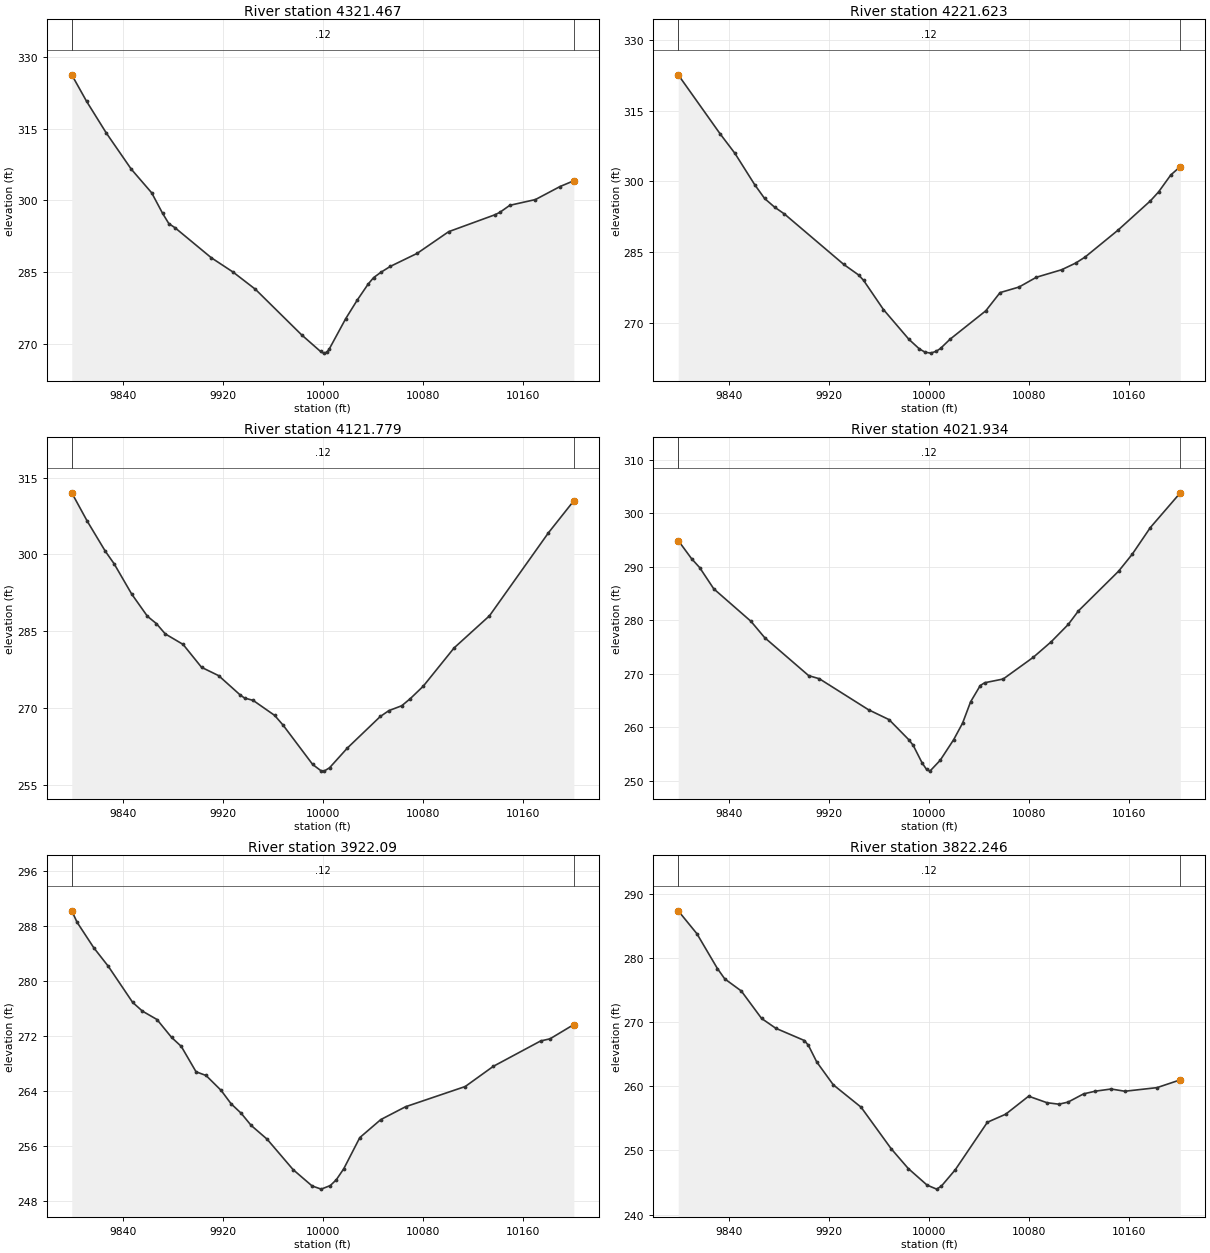
Type RM Length L Ch R = 1 ,4321.467,99.844100,99.844100,99.844100
XS GIS Cut Line= 6
1217281.11663223625345.4845607541217179.18286356625257.320017512
1217117.12170552625192.111719669 1217090.3732621625167.351079343
1217046.48280324625132.1194412461216977.67325241625083.306613471
#Sta/Elev= 30
9799.026326.29499810.941320.7246 9826.57314.16049846.631306.56439862.994301.6093
9871.707297.32579876.722295.16699881.738294.28619910.709288.0225 9928.06285.0419
  9946.1281.40629983.048271.88469998.193268.4074 10000.6 268.06210003.18 268.237
10005.01268.8544 10018.3275.258110027.46279.116910036.21282.475910040.68283.8691
10046.78285.0195 10054.1286.2191 10075.5288.930910100.74293.473510137.64296.9972
10141.66297.508410149.71298.991710170.23 300.19610189.93302.923910200.97304.1323
#Mann= 3 , 0 , 0
9799.026    0.12       09799.026    0.12       010200.97    0.12       0
#XS Ineff= 2 , 0
       0                               0
Bank Sta=9799.026,10200.97
Exp/Cntr=0.3,0.1

Type RM Length L Ch R = 1 ,4221.623,99.844100,99.844100,99.844100
XS GIS Cut Line= 6
1217365.42066222625252.6318842991217227.04352546625158.768584552
1217208.36802412625144.8633294881217194.03926313 625131.65667032
1217173.16306393625117.0666299641217029.29632078625033.277228776
#Sta/Elev= 30
 9799.02322.6097 9832.49310.12469844.383305.9743 9860.24 299.3229868.169296.3995
9876.111294.57189884.027293.1143  9931.6282.40839943.493280.17379947.457 279.022
9963.315272.85389983.674 266.551 9992.06264.51249996.509263.8383   10001263.6189
10005.52263.997510009.01264.621910016.55266.550210045.27272.596310056.66276.4456
10071.85277.629810085.78279.706110106.02281.297910117.41282.7355 10124.9284.0184
10150.97289.658510177.05295.900910183.57 297.78710193.34301.384110200.97303.1625
#Mann= 3 , 0 , 0
 9799.02    0.12       0 9799.02    0.12       010200.97    0.12       0
#XS Ineff= 2 , 0
       0                               0
Bank Sta=9799.02,10200.97
Exp/Cntr=0.3,0.1

Type RM Length L Ch R = 1 ,4121.779,99.844100,99.844100,99.844100
XS GIS Cut Line= 6
1217417.54949401625116.9085899451217364.41160706625088.877473629
1217315.70800742625067.9201107571217154.38359752625022.078403038
1217098.03275229624999.3660967091217043.78459946624973.161904116
#Sta/Elev= 30
9799.047312.01169811.405306.49179825.922300.60719832.954298.16769847.017292.2585
9859.608287.92099866.751286.50279873.895284.48179888.181282.42729902.935277.9615
9916.604276.33839933.879272.56569937.334271.97169944.244271.50669961.455268.5795
9968.217266.67859991.887259.00659998.649257.7572   10001257.7043 10005.4258.3556
10019.67262.214410046.04  268.37 10052.9269.5102 10063.2270.465610070.07271.8597
10080.38274.269510105.14 281.75810133.44288.018910180.59304.203410200.96310.4682
#Mann= 3 , 0 , 0
9799.047    0.12       09799.047    0.12       010200.96    0.12       0
#XS Ineff= 2 , 0
       0                               0
Bank Sta=9799.047,10200.96
Exp/Cntr=0.3,0.1

Type RM Length L Ch R = 1 ,4021.934,99.844100,99.844100,99.844100
XS GIS Cut Line= 6
1217438.03697797625034.1116009081217397.76617228625011.677799442
1217345.56148382 624985.650374741217240.58319791624939.407069131
1217150.34917186624902.5877231331217073.27245627624865.960029508
#Sta/Elev= 30
9799.031294.90759809.719291.50949816.217289.83849827.483285.86819857.232279.7955
 9868.23276.73769903.462 269.6279912.009269.04459951.356263.24559967.812261.3965
9983.549257.65399987.126256.5912 9994.28253.29179997.857252.073310000.53251.7606
10008.74253.788310019.57257.660710026.66260.737810033.11264.737710040.83 267.777
10044.38268.299410059.17268.995410083.35273.071910097.53275.947310111.27279.2072
10119.44281.749610151.56289.167510162.46292.334910176.99297.335910200.98303.8337
#Mann= 3 , 0 , 0
9799.031    0.12       09799.031    0.12       010200.98    0.12       0
#XS Ineff= 2 , 0
       0                               0
Bank Sta=9799.031,10200.98
Exp/Cntr=0.3,0.1

Type RM Length L Ch R = 1 , 3922.09,99.844100,99.844100,99.844100
XS GIS Cut Line= 6
 1217464.1226778624978.7057944381217342.28414057624898.237910824
1217317.12187337624876.6943580551217282.68872587624839.830424431
1217253.34168656 624816.413406251217137.42029788624747.831355195
#Sta/Elev= 30
 9799.04290.21149803.296288.54549816.656284.83469828.331282.12029847.787276.8779
 9855.57275.60959867.244274.38519878.919 271.7829886.701270.46979898.513266.7743
9906.537266.23169918.572264.06769926.595262.10829934.619260.73719942.642258.9606
9955.412256.95619976.217 252.524 9991.42250.1463 9998.71249.683910005.96250.2023
10010.72251.032110016.73252.640410029.61257.190810046.38259.808810066.21261.6797
10114.01264.627910136.45267.563210174.36271.2617 10181.9271.574410200.94273.6535
#Mann= 3 , 0 , 0
 9799.04    0.12       0 9799.04    0.12       010200.94    0.12       0
#XS Ineff= 2 , 0
       0                               0
Bank Sta=9799.04,10200.94
Exp/Cntr=0.3,0.1

Type RM Length L Ch R = 1 ,3822.246,99.844100,99.844100,99.844100
XS GIS Cut Line= 6
1217540.40871258624892.1685122971217470.34280562624845.210648071
1217369.90897969624787.9408431541217368.20433421 624786.89481076
1217358.08218432624780.9513000771217189.77545162624696.654937769
#Sta/Elev= 30
9799.039287.37899813.964283.81499830.396278.37619836.289276.7601 9849.51274.8755
9865.755270.59259877.157269.05419900.089267.1396 9903.31266.36929909.933263.7961
9923.179260.2323 9945.41 256.7449969.542250.25319983.178247.17699998.285244.5834
10005.91  243.9610009.72244.433310020.83246.984110046.52254.393710061.19255.6505
10079.54258.459310094.22257.443310103.74257.211210111.07 257.53410123.57258.8243
10133.05259.246310145.59259.5796 10156.6259.231810182.28259.792910200.97261.0113
#Mann= 3 , 0 , 0
9799.039    0.12       09799.039    0.12       010200.97    0.12       0
#XS Ineff= 2 , 0
       0                               0
Bank Sta=9799.039,10200.97
Exp/Cntr=0.3,0.1

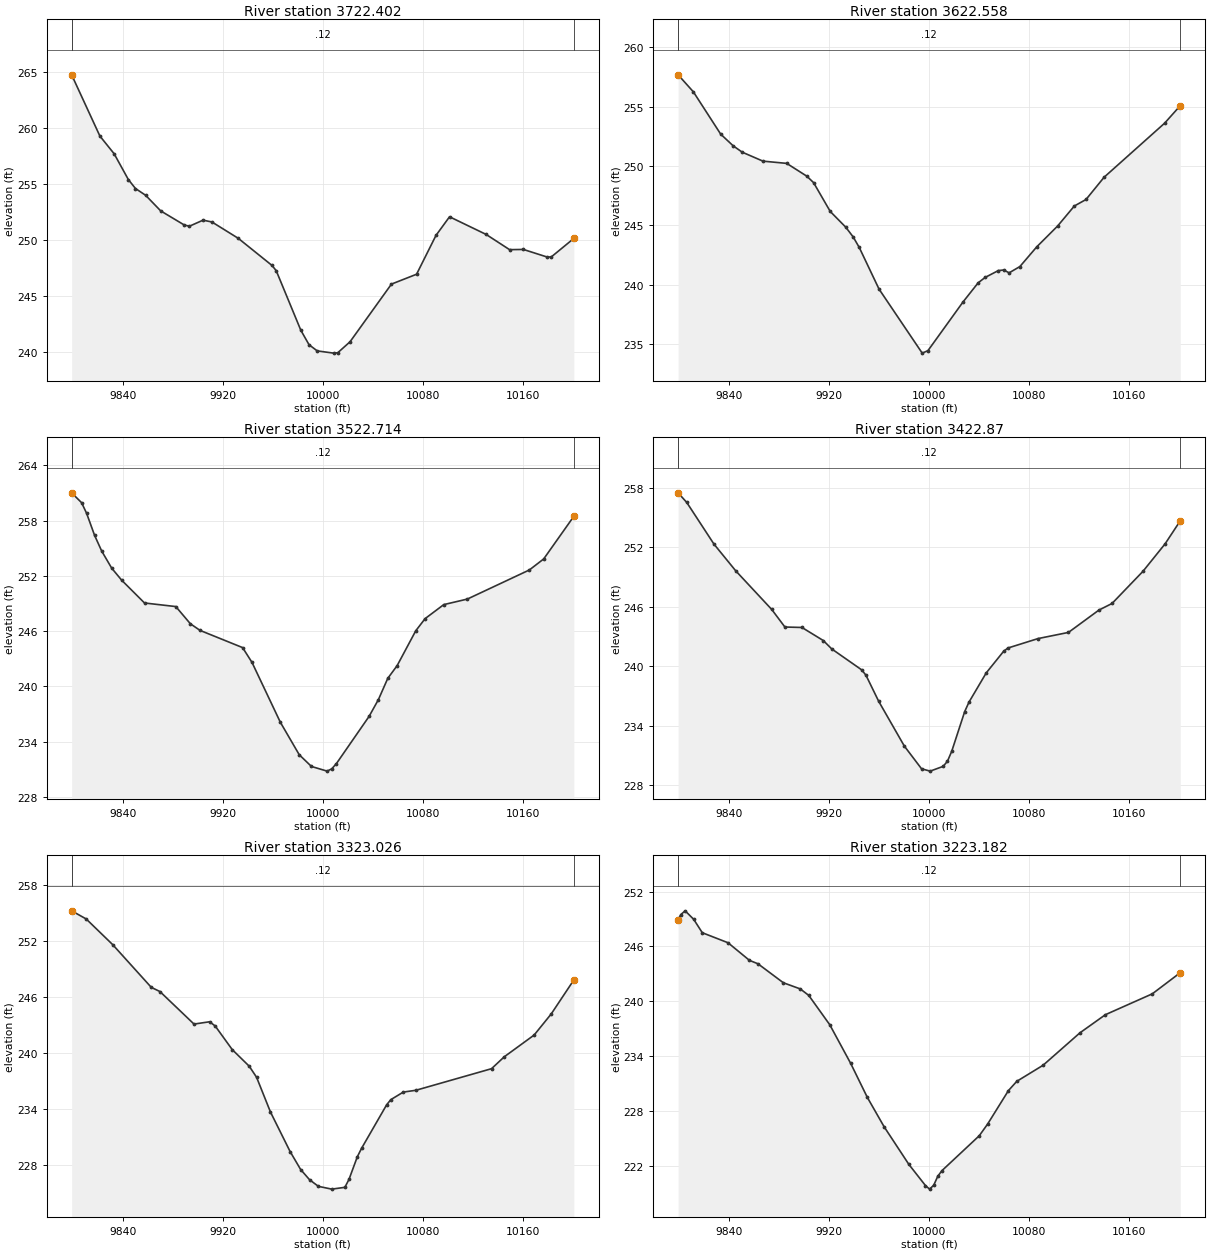
Type RM Length L Ch R = 1 ,3722.402,99.844200,99.844200,99.844200
XS GIS Cut Line= 6
1217565.06784105 624768.275265621217507.06278415624724.389454582
1217457.55800701624699.776961634 1217315.4219659624683.741104696
1217259.19779775624663.4926275421217196.92575397624631.220777092
#Sta/Elev= 30
 9799.15264.7621 9821.73   259.39833.152257.7156 9844.53255.41219850.219 254.616
9858.347254.01019870.395252.6184 9889.28251.3579 9893.36251.2515 9904.27251.7909
9911.387251.62899932.453250.16929959.418247.75089962.773 247.2889982.466241.9719
 9989.03240.67839995.594240.123210008.72239.9244   10012239.954910021.85240.9374
10054.98246.084510075.08246.965310090.61 250.43210101.45252.093410130.75250.5163
10149.47249.159410160.56249.177310179.03 248.51910182.73248.498310200.89250.1621
#Mann= 3 , 0 , 0
 9799.15    0.12       0 9799.15    0.12       010200.89    0.12       0
#XS Ineff= 2 , 0
       0                10056.58       0
Bank Sta=9799.15,10200.89
Exp/Cntr=0.3,0.1

Type RM Length L Ch R = 1 ,3622.558,99.844100,99.844100,99.844100
XS GIS Cut Line= 6
1217560.13316098 624739.819243031217434.40209665624636.070716536
1217422.51684708624620.4605622311217407.53531923624585.889921371
1217390.21806388624560.0924246191217289.81464813624448.249878591
#Sta/Elev= 30
9799.112 257.6949811.317256.25959833.182252.69369843.203 251.7059850.399251.1736
9866.971250.41869885.999 250.2299902.117249.1478 9907.49248.60749920.829246.1769
9933.258244.84849939.171244.02979944.038243.14359959.867239.63199994.419234.2334
    9999234.441410027.06238.544410039.16240.157410044.72240.612210055.36241.1937
10059.66241.240110063.97241.001910072.58241.531610086.08243.194410102.74244.9464
10116.14246.635410125.49247.185310139.99249.064210188.35253.614910200.93255.0976
#Mann= 3 , 0 , 0
9799.112    0.12       09799.112    0.12       010200.93    0.12       0
#XS Ineff= 2 , 0
       0                               0
Bank Sta=9799.112,10200.93
Exp/Cntr=0.3,0.1

Type RM Length L Ch R = 1 ,3522.714,99.844100,99.844100,99.844100
XS GIS Cut Line= 6
1217604.18952395 624723.755559471217569.64384882624674.592061403
1217545.96284659624637.0999254981217502.54414117624561.087175333
1217446.82302595624457.8182403581217399.34422603624378.265532143
#Sta/Elev= 30
9799.014  261.019806.988259.93729810.998258.78129817.386256.38919823.093 254.682
9831.047 252.8389839.067251.52489857.332249.05399882.398248.66389894.039246.7978
  9901.8246.07739935.849244.21059943.405242.59579966.075236.10359981.189232.5797
9990.985231.3077 10003.5 230.80310007.23231.055310010.97231.628310037.11236.7497
10044.58238.574710052.05240.874610059.52 242.24910074.46246.037610081.93247.3565
10096.87248.876810115.72249.477310165.38252.637710176.85253.834510200.98258.4615
#Mann= 3 , 0 , 0
9799.014    0.12       09799.014    0.12       010200.98    0.12       0
#XS Ineff= 2 , 0
       0                               0
Bank Sta=9799.014,10200.98
Exp/Cntr=0.3,0.1

Type RM Length L Ch R = 1 , 3422.87,99.844100,99.844100,99.844100
XS GIS Cut Line= 6
1217658.66950072624710.3823755871217639.02825863624668.685448061
1217625.23004634624632.9940801861217598.99394016624541.889795261
1217564.05297789624435.1734642531217524.90735186624331.868678187
#Sta/Elev= 30
 9799.04257.47849805.976256.50349827.735252.30719845.131 249.6169873.986 245.714
9884.505243.94519898.161243.90019915.232242.58199922.061241.7304 9945.96 239.626
9949.374239.08779959.616236.44559980.119231.93579993.898 229.64610000.79229.4126
10011.15229.891710014.61230.407710018.06231.421610028.42235.418710031.88236.3785
10045.69239.324810059.51241.487210062.96241.825510087.14242.780410111.47243.4008
10135.83245.652210146.36246.3213 10171.1249.562310188.77252.326110200.99254.6635
#Mann= 3 , 0 , 0
 9799.04    0.12       0 9799.04    0.12       010200.99    0.12       0
#XS Ineff= 2 , 0
       0                               0
Bank Sta=9799.04,10200.99
Exp/Cntr=0.3,0.1

Type RM Length L Ch R = 1 ,3323.026,99.844100,99.844100,99.844100
XS GIS Cut Line= 6
1217745.44084717 624705.254951661217721.60965052624636.478740665
1217694.85991773 624538.033804391217679.07599815624499.870210846
1217660.38539844624403.3088262371217636.74123844624319.185929178
#Sta/Elev= 30
9799.069255.19619810.699254.32679831.866251.58639862.783247.01149869.727246.5617
 9896.97243.08269909.508243.33069913.969242.87159927.568240.35179941.167238.5764
9947.044237.39359958.166233.67359973.871229.44979982.314 227.5269989.407226.4389
9996.499225.725610007.21 225.42910017.68225.620210021.02226.4807 10027.7228.9044
10031.05229.7936 10051.1234.442810054.44234.998110064.46235.810110074.49236.0006
10135.06238.311510145.28239.587510169.14241.910110182.77244.159210200.91247.8022
#Mann= 3 , 0 , 0
9799.069    0.12       09799.069    0.12       010200.91    0.12       0
#XS Ineff= 2 , 0
       0                               0
Bank Sta=9799.069,10200.91
Exp/Cntr=0.3,0.1

Type RM Length L Ch R = 1 ,3223.182,99.844100,99.844100,99.844100
XS GIS Cut Line= 6
1217825.62872586624679.9474357131217794.89912402624571.122475393
1217785.10205877624522.067985232 1217768.4697112624412.741541444
1217755.79920171624359.3029552171217735.59809823624288.869334984
#Sta/Elev= 30
9799.027248.9108 9801.21249.48079804.643249.89079811.509248.95969818.375247.4963
9838.972246.40129856.137244.47399862.948244.10029883.257 242.0269896.796241.3535
9903.566240.64849920.393237.43899937.121233.22029950.504229.48529963.869226.2918
9983.741222.16329996.989219.857210000.29219.4639 10003.6219.886810006.91220.8831
10010.21221.486910040.07225.301910046.74226.574610063.42230.238910070.09231.2491
10091.16233.009110120.64236.551210141.03238.535210178.57240.815910200.98243.1313
#Mann= 3 , 0 , 0
9799.027    0.12       09799.027    0.12       010200.98    0.12       0
#XS Ineff= 2 , 0
       0                               0
Bank Sta=9799.027,10200.98
Exp/Cntr=0.3,0.1

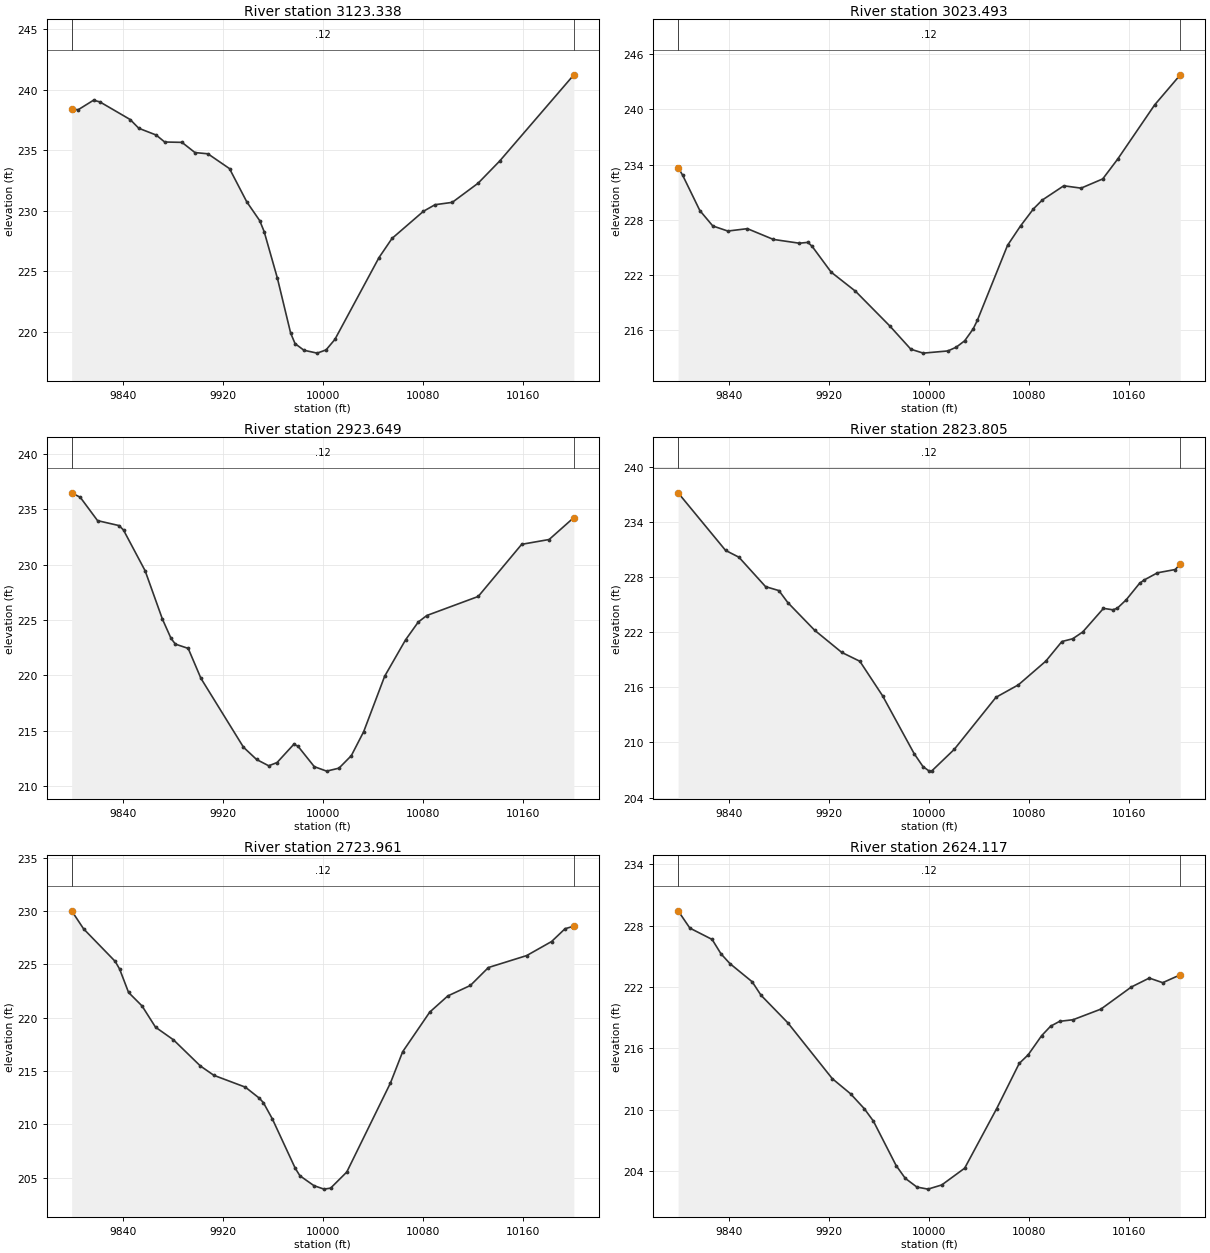
Type RM Length L Ch R = 1 ,3123.338,99.844100,99.844100,99.844100
XS GIS Cut Line= 6
1217943.63972085624659.9645390231217896.03510115 624516.70810722
1217877.76497012624471.2216316551217876.92274746624469.407613743
1217858.86018305624423.8442758081217812.81433647624280.078436317
#Sta/Elev= 30
9799.023238.37119804.364 238.3569816.544239.13629821.651238.99549845.851237.5405
9852.766236.81719866.595236.26169873.509 235.6829887.338235.6538 9897.71234.8106
9908.081234.70779925.368233.48429939.197230.73559949.568229.18079953.094228.2806
9963.701224.42869974.308219.89059977.844219.02119984.915218.47469995.522218.2357
10002.63218.500810009.69219.363910044.99 226.12610055.44227.7144 10080.6229.9589
10089.89230.501110103.67230.694910124.34232.277410141.57234.105310200.97241.2339
#Mann= 3 , 0 , 0
9799.023    0.12       09799.023    0.12       010200.97    0.12       0
#XS Ineff= 2 , 0
       0                               0
Bank Sta=9799.023,10200.97
Exp/Cntr=0.3,0.1

Type RM Length L Ch R = 1 ,3023.493,99.844200,99.844200,99.844200
XS GIS Cut Line= 6
1218022.91676987624618.8822071751217969.97368229624460.711867244
1217965.47488894624437.6881029951217965.77103975624410.644612881
1217960.06588905624386.7295935371217908.93160986624235.179375993
#Sta/Elev= 30
9799.065233.68059802.605232.86569816.444229.01259826.824227.33799838.837226.7882
9854.502227.0453 9875.26225.87929896.018225.46779902.938225.55899906.398 225.111
9921.526 222.3299940.995220.25779968.578216.47119985.293 213.9669995.211213.5419
10014.92213.778610021.62214.186810028.37  214.8810035.11216.156610038.49217.0908
10062.66225.234110073.05227.338610083.43 229.19610090.36230.139810107.67231.6973
10121.52231.442610138.84232.441610150.69 234.57110180.39240.474710200.92243.7359
#Mann= 3 , 0 , 0
9799.065    0.12       09799.065    0.12       010200.92    0.12       0
#XS Ineff= 2 , 0
       0                               0
Bank Sta=9799.065,10200.92
Exp/Cntr=0.3,0.1

Type RM Length L Ch R = 1 ,2923.649,99.844100,99.844100,99.844100
XS GIS Cut Line= 6
1218109.68617177624599.1100398331218066.41827493624459.663950621
1218060.48466982624427.0835215421218056.00761223624374.052828733
1218047.56626957624333.5978920861218006.91025791624212.063851104
#Sta/Elev= 30
 9799.04236.49639805.947236.09069819.785233.98369837.082233.53449840.542233.1325
9857.839229.45839871.677225.09019878.596223.34419882.056222.83049892.306222.4445
9902.519219.73599936.561213.51619947.054212.40779956.743211.84089963.413212.1303
9976.752213.77069980.062 213.6239993.228211.7612 10003.1211.357210012.98211.6255
10022.86212.753910032.77214.925710049.53219.924410066.29223.219510076.42224.8213
10083.28225.414910124.43227.135510159.22231.845310181.18232.280110200.95234.2599
#Mann= 3 , 0 , 0
 9799.04    0.12       0 9799.04    0.12       010200.95    0.12       0
#XS Ineff= 2 , 0
       0                               0
Bank Sta=9799.04,10200.95
Exp/Cntr=0.3,0.1

Type RM Length L Ch R = 1 ,2823.805,99.844100,99.844100,99.844100
XS GIS Cut Line= 6
1218235.36293148624565.2596963811218194.92280954624468.766141191
1218160.37364865624395.294937515 1218149.8401137624369.456400186
1218112.94579169 624295.388633061218071.35027942624198.439211632
#Sta/Elev= 30
9799.014 237.1519837.003 230.8869847.675230.14789869.019226.94369879.691226.5149
9886.805 225.2119908.236222.20789929.989219.7905 9944.49218.82499962.618215.0813
9987.926208.78089995.016207.367810000.06206.873510002.07 206.89710020.06209.2432
10053.46214.909310071.37216.259910093.36218.843510106.21220.974510114.84221.2731
10122.85222.007610139.49224.581210146.97224.425910150.54224.593210157.68225.5128
10168.39227.309810171.96227.659410182.67228.449810196.95228.808110200.98229.4195
#Mann= 3 , 0 , 0
9799.014    0.12       09799.014    0.12       010200.98    0.12       0
#XS Ineff= 2 , 0
       0                               0
Bank Sta=9799.014,10200.98
Exp/Cntr=0.3,0.1

Type RM Length L Ch R = 1 ,2723.961,99.844100,99.844100,99.844100
XS GIS Cut Line= 6
1218317.71958697624502.8942706761218248.38655876624348.176118645
1218233.74247631624321.5116596821218232.64324326624319.840825548
1218204.22542174624267.8196262511218145.44451405624140.014230717
#Sta/Elev= 30
9799.036230.01199808.635228.31659833.802225.28189837.397224.56119844.587222.3597
9855.373221.09629866.158219.10449880.539217.9166 9902.11215.46249912.896 214.589
9938.062213.48139949.093212.46149952.443212.03819959.633210.51269977.981205.8777
9981.724205.17439992.953204.2465   10001203.921810006.29204.015810019.23205.5253
10054.19213.876210063.96216.803410085.62 220.51710100.07 222.03210118.13223.0136
10132.57224.696310163.22225.817110183.13227.133610193.96228.338410200.95228.5707
#Mann= 3 , 0 , 0
9799.036    0.12       09799.036    0.12       010200.95    0.12       0
#XS Ineff= 2 , 0
       0                               0
Bank Sta=9799.036,10200.95
Exp/Cntr=0.3,0.1

Type RM Length L Ch R = 1 ,2624.117,116.203900,116.203900,116.203900
XS GIS Cut Line= 6
1218409.56154121624479.8443161551218362.56945046624368.326034778
1218327.93262077 624297.36100794 1218327.0588128624295.561991647
1218300.85865811624242.6411585181218243.68920267624113.815991111
#Sta/Elev= 30
9799.018229.46359808.433 227.7729826.234226.66389833.355225.25339840.475224.3013
9858.276222.52399865.396221.19899886.758218.51459922.419  213.049937.022211.5613
9947.974210.10929955.276208.8966 9973.53204.53419980.831203.2856 9990.15202.4305
    9999202.227610010.06202.637810028.37204.275310053.99210.102210072.06214.5318
10079.24215.3755   10090217.247110097.18218.172310104.36218.648410115.13218.8047
10137.41219.843210161.79222.008810176.15222.883310186.92 222.43210200.99223.2043
#Mann= 3 , 0 , 0
9799.018    0.12       09799.018    0.12       010200.99    0.12       0
#XS Ineff= 2 , 0
       0                               0
Bank Sta=9799.018,10200.99
Exp/Cntr=0.3,0.1

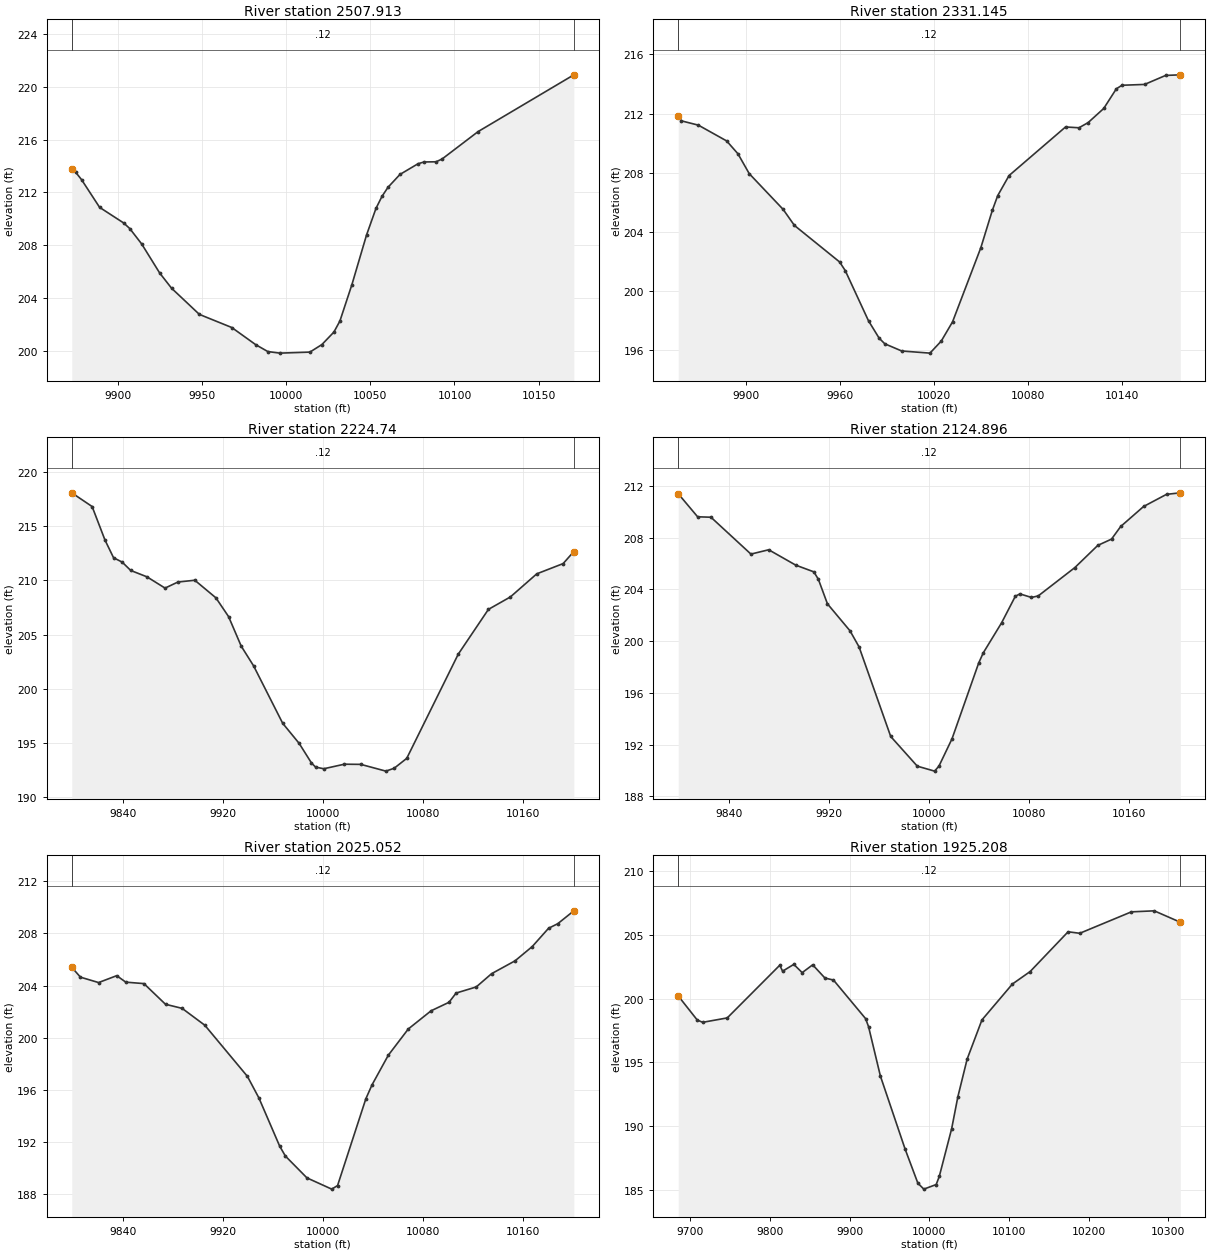
Type RM Length L Ch R = 1 ,2507.913,176.768000,176.768000,176.768000
XS GIS Cut Line= 2
1218476.70535779624355.1348423661218358.43073869624080.952770814
#Sta/Elev= 30
9872.387213.74179874.648213.53319878.221212.9626 9888.94210.86699903.233209.6858
9906.868209.26359913.952208.09729924.671205.89529931.717 204.7469948.283202.7599
9967.548201.7677 9981.84 200.4639988.986199.94669996.133199.8275   10014199.9048
10021.14200.475410028.29201.423110031.86202.259810039.01 205.02110047.68208.7657
 10053.3210.785210056.87 211.69610060.45212.383610067.59213.360610078.31214.1686
10081.89214.303810089.03214.316910092.61214.526210114.04216.603510170.99 220.903
#Mann= 3 , 0 , 0
9872.387    0.12       09872.387    0.12       010170.99    0.12       0
#XS Ineff= 2 , 0
       0                               0
Bank Sta=9872.387,10170.99
Exp/Cntr=0.3,0.1

Type RM Length L Ch R = 1 ,2331.145,106.404600,106.404600,106.404600
XS GIS Cut Line= 2
1218644.70907807624318.8460387891218511.65013158 624027.19158031
#Sta/Elev= 30
9856.668211.8105 9858.73211.50259869.549211.21179887.579210.14499894.792209.2746
9902.004207.92949923.641205.51149930.853204.42539959.702201.95249963.308201.3678
9978.161197.96679984.945196.79419988.551196.4132 9999.37195.9254 10017.4 195.781
10024.61196.597610031.82197.899510049.86202.912110057.21205.446110060.67206.4465
10067.89207.801110103.95211.089410112.54211.035910118.37211.384510128.34212.3413
 10136.4213.674610140.01 213.91310154.43213.969710167.87 214.57910177.24214.6195
#Mann= 3 , 0 , 0
9856.668    0.12       09856.668    0.12       010177.24    0.12       0
#XS Ineff= 2 , 0
       0                               0
Bank Sta=9856.668,10177.24
Exp/Cntr=0.3,0.1

Type RM Length L Ch R = 1 , 2224.74,99.844100,99.844100,99.844100
XS GIS Cut Line= 6
1218733.43390102624365.3423746521218696.40124333624235.825234385
 1218686.6406646 624141.523715691218679.65963533624104.612604069
1218661.71662585624046.4231097471218635.01216645623977.615837946
#Sta/Elev= 30
9799.034218.11269815.325216.84369825.627213.74089832.494212.10399839.362211.7022
 9846.23210.92879859.199210.34029873.701209.2966    9884209.85849897.519210.0232
9914.418208.39559924.557206.6591 9934.68203.92469944.642202.08939967.887196.7839
9981.049194.92749990.916193.11399994.205192.732110000.78192.579210017.23     193
10030.42192.984410050.46192.359310057.13192.626610067.18193.541810108.38203.1768
10132.54207.325710150.14208.478510171.25210.615610192.37211.564210200.94212.6821
#Mann= 3 , 0 , 0
9799.034    0.12       09799.034    0.12       010200.94    0.12       0
#XS Ineff= 2 , 0
       0                               0
Bank Sta=9799.034,10200.94
Exp/Cntr=0.3,0.1

Type RM Length L Ch R = 1 ,2124.896,99.844100,99.844100,99.844100
XS GIS Cut Line= 6
1218858.35441651624321.4435755311218829.91390687624253.413692993
1218784.63754768624156.0817717841218778.06419013624136.277082789
 1218767.7409317624107.7337561011218691.94786558 623956.03202732
#Sta/Elev= 30
 9799.04211.40019814.557209.61779825.225209.58439857.229206.73419871.453207.0689
 9893.14205.87879907.614205.36049911.232204.78139918.469202.88969936.562   200.8
9943.798199.55759969.127192.63479990.395190.340710004.23189.956910007.72190.3435
10018.18192.453510039.51198.307310043.18199.095510057.85 201.41710068.85203.4714
10072.52 203.65810081.79203.382810087.19   203.510116.53205.692310134.87207.4068
10145.87207.892510153.21208.867910171.54210.413510189.88211.352810200.93211.4702
#Mann= 3 , 0 , 0
 9799.04    0.12       0 9799.04    0.12       010200.93    0.12       0
#XS Ineff= 2 , 0
       0                               0
Bank Sta=9799.04,10200.93
Exp/Cntr=0.3,0.1

Type RM Length L Ch R = 1 ,2025.052,99.844100,99.844100,99.844100
XS GIS Cut Line= 6
1218972.13817676624251.0835047271218946.21355959624196.161624627
1218918.71955313624151.1382966351218889.98131455624115.094910197
1218806.86367061624027.5576883151218741.58606844623925.268737302
#Sta/Elev= 30
9799.099205.39529806.057204.64099820.569 204.2289835.081204.75599842.337204.2592
9856.848204.14869874.117202.56519887.424202.25279905.592200.9601 9939.67197.0445
9948.841195.39889965.451191.71179970.058190.94379987.324189.270910007.17188.4098
10011.83188.683310034.48195.332410039.42196.396110052.46198.666210068.45200.6745
10086.66 202.06510101.03202.7171 10106.7203.423510122.83203.8926 10135.1204.9074
10153.91205.893710167.64206.984710180.69208.383810188.07208.736110200.94209.7214
#Mann= 3 , 0 , 0
9799.099    0.12       09799.099    0.12       010200.94    0.12       0
#XS Ineff= 2 , 0
       0                               0
Bank Sta=9799.099,10200.94
Exp/Cntr=0.3,0.1

Type RM Length L Ch R = 1 ,1925.208,133.973400,133.973400,133.973400
XS GIS Cut Line= 6
1219048.57078931624297.243581396 1219013.5099375624185.910108466
1218978.29364537624100.504978842 1218954.4639289624055.345370977
 1218866.0216409623912.0983131611218780.99408037623729.300722484
#Sta/Elev= 30
9684.869200.20589708.753 198.3189715.589198.13999746.396198.48469812.352202.6132
9815.868202.14419829.931 202.6799840.479202.03259853.646202.64439869.013201.6102
9879.765201.4496 9920.07198.4292 9923.78197.79939938.618193.93789969.626188.2166
9985.694185.53659993.161185.071110008.66  185.4310012.55186.0605 10028.1189.8032
10035.88192.299510047.55195.2592 10066.1198.324610104.41201.141510126.67202.1185
10174.28205.232110188.93205.114810253.73206.793710282.43206.874110315.15205.9811
#Mann= 3 , 0 , 0
9684.869    0.12       09684.869    0.12       010315.15    0.12       0
#XS Ineff= 2 , 0
       0                               0
Bank Sta=9684.869,10315.15
Exp/Cntr=0.3,0.1

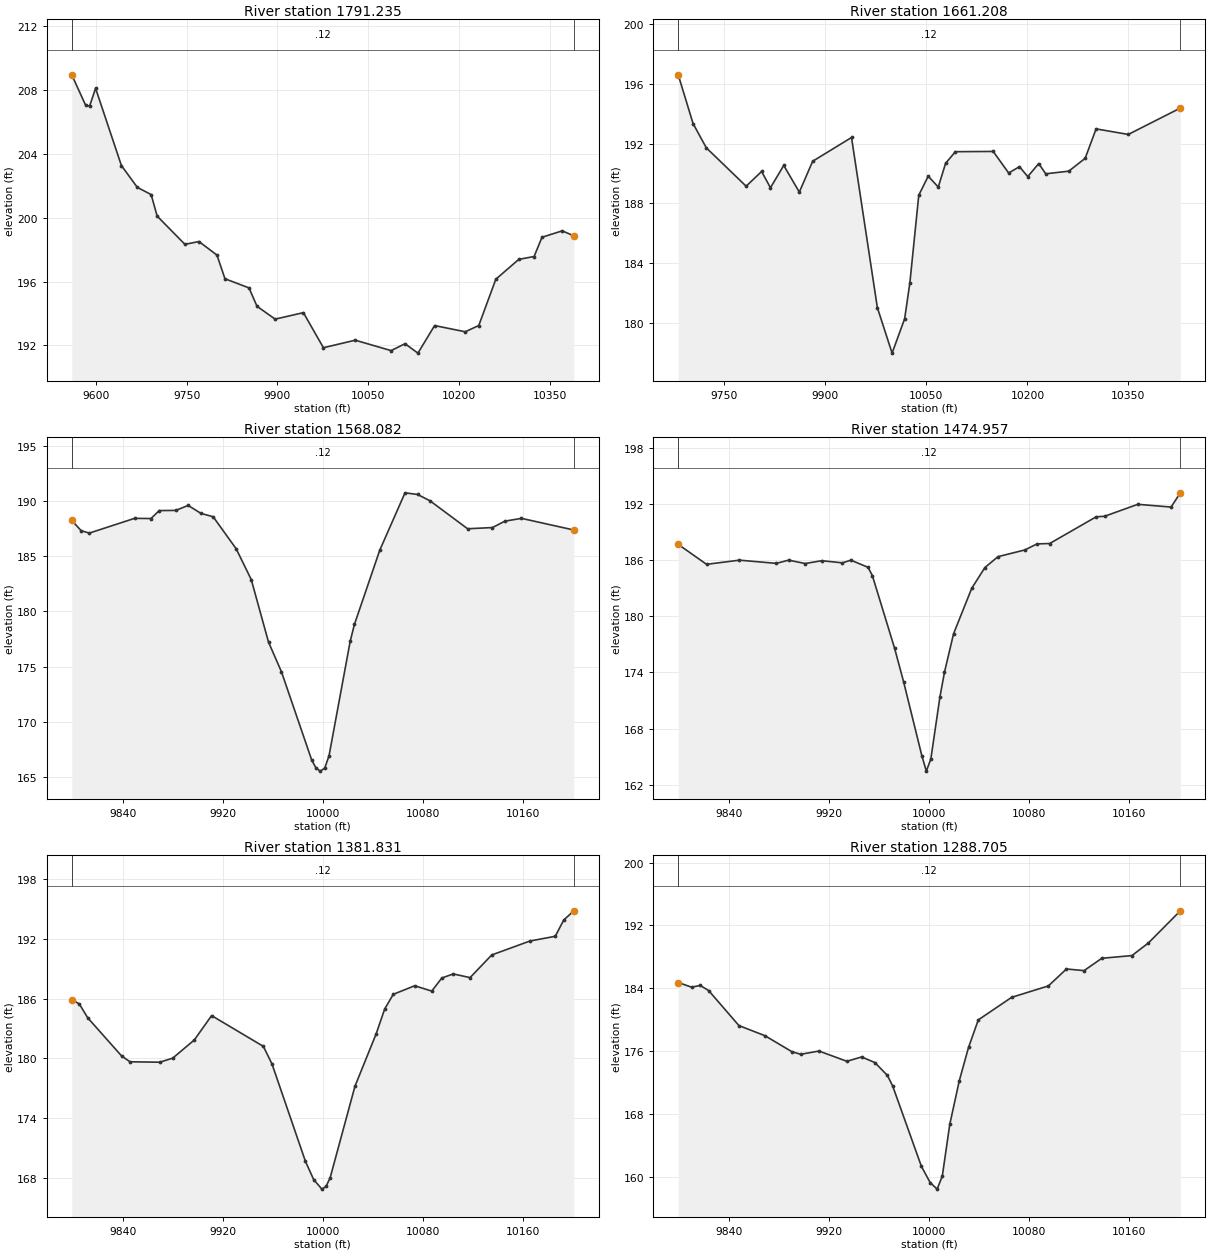
Type RM Length L Ch R = 1 ,1791.235,130.026600,130.026600,130.026600
XS GIS Cut Line= 6
1219088.18791467624428.4984927331219089.43317157624245.445727751
 1219074.4900887624128.3915786591219057.05649203624030.016283184
1219044.60392302 623859.416087241218882.72052538623658.929725572
#Sta/Elev= 30
9560.253208.9691  9583.2207.05729589.762207.01149599.605208.12419642.256203.2841
9668.504201.9152 9691.47201.46019701.313200.11279747.277198.34039770.429198.5173
9800.197197.66689813.426196.18369853.116195.61049866.383194.45599896.371193.6514
9943.018194.05899976.133191.858810028.72192.331510087.96 191.67810111.01192.1105
10132.29191.520610159.86193.249110210.46192.859610232.86193.252310261.06196.1555
10299.01197.399110324.31197.578510337.31198.7851 10370.7199.186910389.97198.8752
#Mann= 3 , 0 , 0
9560.253    0.12       09560.253    0.12       010389.97    0.12       0
#XS Ineff= 2 , 0
       0                10060.07       0
Bank Sta=9560.253,10389.97
Exp/Cntr=0.3,0.1

Type RM Length L Ch R = 1 ,1661.208,93.125700,93.125700,93.125700
XS GIS Cut Line= 6
1219237.70423979624286.4850531221219231.39705428624136.796073392
1219225.05241394624083.9731262771219208.86139709624025.100998774
1219128.61049902623880.8617713451218942.49285683623625.307789162
#Sta/Elev= 30
9681.372196.6169  9703.4193.35119723.103191.7249 9782.21189.15529805.196190.1409
9818.331189.05289838.077190.54749861.208188.75939881.034190.82679938.732 192.419
9977.111181.0208    9999177.972210017.66180.278810025.43 182.69610038.61  188.55
10052.62189.825110067.56189.099510078.46190.6889   10093191.467310149.16191.4841
10172.09 190.04110188.17190.4633 10200.5189.796710216.74190.674510227.18189.9857
10261.38190.162810285.74191.023810301.97192.995810349.79192.623310427.05194.3895
#Mann= 3 , 0 , 0
9681.372    0.12       09681.372    0.12       010427.05    0.12       0
#XS Ineff= 2 , 0
       0                               0
Bank Sta=9681.372,10427.05
Exp/Cntr=0.3,0.1

Type RM Length L Ch R = 1 ,1568.082,93.125600,93.125600,93.125600
XS GIS Cut Line= 6
1219275.20314105624104.6798167161219272.74813174624047.307133112
1219266.53739611623999.3250391421219237.17019237623902.573085098
1219225.08793342623854.7546412281219201.15434677623711.205277502
#Sta/Elev= 30
 9799.08188.25699806.614187.32989813.181187.11279849.303188.44789862.483 188.433
9869.099189.15439882.332189.17019892.257189.62399902.438188.90299912.265188.5949
9930.722185.68169942.758182.89179956.564177.22059966.918174.52639991.079166.5358
 9994.53165.79839997.982165.507810001.58165.780610005.03166.912110021.97177.3031
10025.36178.830410045.66185.569610065.83190.765910075.85190.618710085.87190.0398
10115.94187.503910135.85187.6142 10145.8188.194810159.07188.448710200.98187.3906
#Mann= 3 , 0 , 0
 9799.08    0.12       0 9799.08    0.12       010200.98    0.12       0
#XS Ineff= 2 , 0
       0                               0
Bank Sta=9799.08,10200.98
Exp/Cntr=0.3,0.1

Type RM Length L Ch R = 1 ,1474.957,93.125700,93.125700,93.125700
XS GIS Cut Line= 6
 1219291.5612048624129.6371878241219296.66069584624034.893998698
1219302.39699359 623995.49494869  1219356.822574  623863.7086767
1219370.31632322623812.2835565791219382.34999395623742.119877912
#Sta/Elev= 30
9799.078187.66669821.752185.53639848.036185.98169877.606185.63959887.463185.9839
9900.666185.62269913.928185.92369930.505185.69619937.264185.98089951.032185.2154
9954.474184.32769972.216  176.599979.485172.98429994.023165.12139997.657163.4564
10001.27164.757110008.55171.390210012.18174.017410019.46178.130510034.01182.9805
10044.52 185.19210055.03186.356210076.58 187.07510086.24187.716810096.41187.7594
10133.65190.614310140.31190.665410166.94191.943710193.57191.650710200.94193.1709
#Mann= 3 , 0 , 0
9799.078    0.12       09799.078    0.12       010200.94    0.12       0
#XS Ineff= 2 , 0
       0                               0
Bank Sta=9799.078,10200.94
Exp/Cntr=0.3,0.1

Type RM Length L Ch R = 1 ,1381.831,93.125700,93.125700,93.125700
XS GIS Cut Line= 6
1219359.15159524624162.0408314051219373.79620445624103.777353028
1219404.78237832624009.366642718 1219416.5661649623934.395571103
1219448.55228026623828.7447637141219462.16794469623774.327949908
#Sta/Elev= 30
9799.049185.88459805.063185.47749811.828184.07579838.891180.25389845.657179.6633
9869.549179.61899879.908180.03099897.173181.85769910.985184.29869952.422181.2098
9959.305179.45069986.065169.67599992.665167.83939999.263166.874710002.56167.1399
10005.85168.005210025.77 177.21610042.68 182.45510049.54  184.9610056.39186.4335
10073.53187.295510087.24186.760610095.25188.070610104.38188.484410117.89188.1148
10135.23190.3884 10165.8191.787710186.09192.262910192.86 193.89710200.96194.8198
#Mann= 3 , 0 , 0
9799.049    0.12       09799.049    0.12       010200.96    0.12       0
#XS Ineff= 2 , 0
       0                               0
Bank Sta=9799.049,10200.96
Exp/Cntr=0.3,0.1

Type RM Length L Ch R = 1 ,1288.705,93.125700,93.125700,93.125700
XS GIS Cut Line= 6
1219398.27456675624182.8849871491219447.72435831624058.003888467
1219471.57778181624025.8620844421219514.81040505623988.023522601
1219537.41468624623953.5190128131219583.12416855623833.958102311
#Sta/Elev= 30
9799.093 184.7299809.787184.13879816.618184.3592 9823.45183.70619847.659179.2517
9868.561177.95779889.929175.93889897.093175.59639911.719176.01189934.063174.7078
9945.874  175.269956.454 174.5469966.498172.91229970.768171.54219993.727161.3291
10000.71159.2772 10006.3158.438410010.44160.098910016.42166.683510024.04172.2325
10031.42176.467310039.26179.977710065.95182.846210095.36 184.29910109.79186.4528
10123.93186.245110138.08187.814110162.23188.159110175.39 189.76310200.93193.8537
#Mann= 3 , 0 , 0
9799.093    0.12       09799.093    0.12       010200.93    0.12       0
#XS Ineff= 2 , 0
       0                               0
Bank Sta=9799.093,10200.93
Exp/Cntr=0.3,0.1