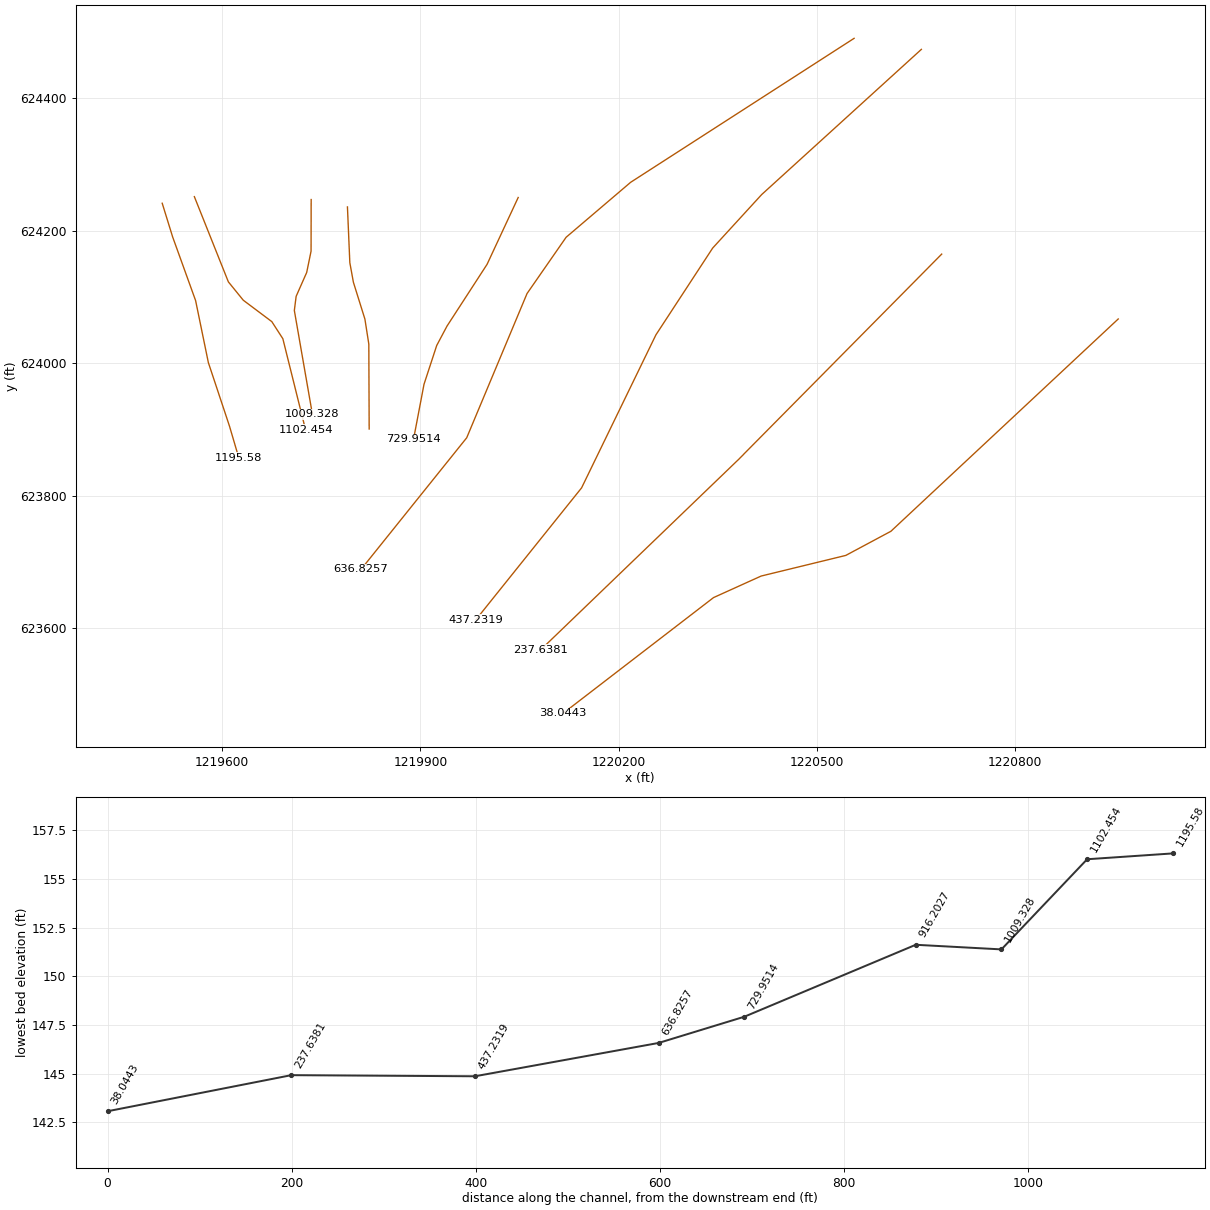
HEC-RAS study 222_ras.prj: 222

--- 222_ras.g01 (geometry) --- (continued)

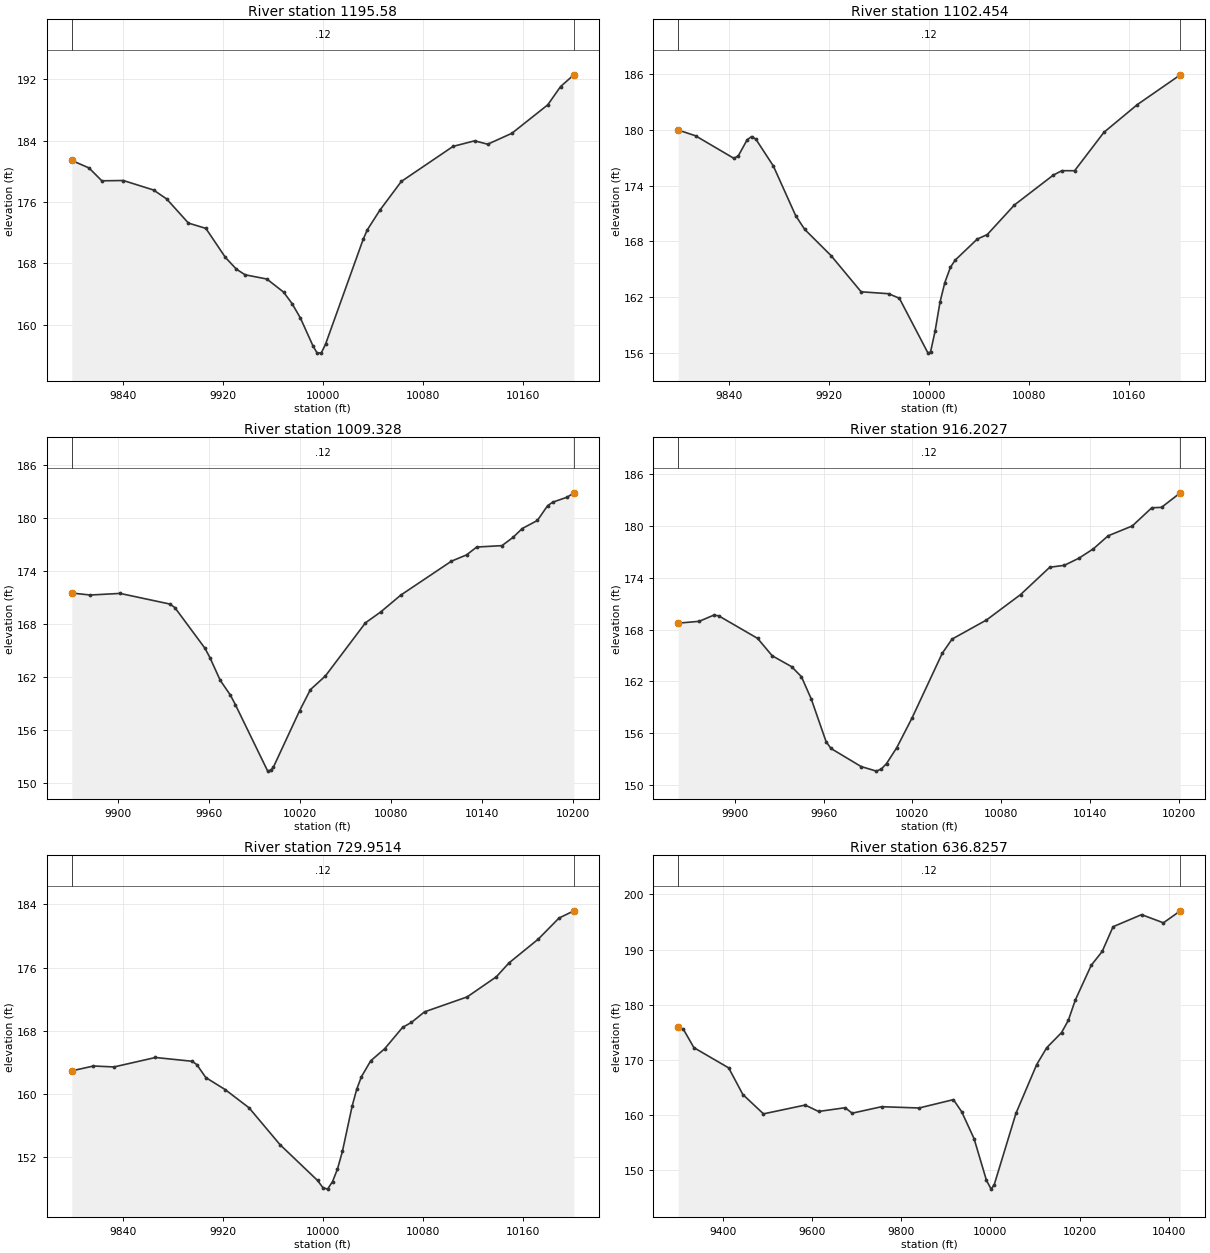
Type RM Length L Ch R = 1 , 1195.58,93.125600,93.125600,93.125600
XS GIS Cut Line= 6
1219509.52135832 624241.534703531219525.30837617624190.653081462
 1219560.0526819624094.5707941711219579.31809169624001.043268875
1219611.37648881623904.787358468 1219625.3683453623857.316448202
#Sta/Elev= 30
9799.064181.4082 9812.83 180.4379823.135178.75869840.311178.79869864.544177.5597
 9875.01176.39689892.454173.25239906.409172.55989922.018168.7845 9930.83167.2501
9937.808 166.5169955.223165.96599968.644164.25449975.355162.77389982.065160.8907
9992.131157.25849995.486156.31139998.841156.355510002.18157.468710032.29171.1239
10035.64172.377410045.67174.927310062.82178.670310104.31183.2471 10121.6183.9684
10131.98183.524510151.34184.948110180.07188.656210190.34191.041310200.95 192.565
#Mann= 3 , 0 , 0
9799.064    0.12       09799.064    0.12       010200.95    0.12       0
#XS Ineff= 2 , 0
       0                               0
Bank Sta=9799.064,10200.95
Exp/Cntr=0.3,0.1

Type RM Length L Ch R = 1 ,1102.454,93.125700,93.125700,93.125700
XS GIS Cut Line= 6
1219558.15919952624251.4906220951219609.58899063624122.867933521
1219632.14547283624095.1549603941219675.32383297624062.826811739
1219692.02473069624037.0477602951219726.38704381623899.418764765
#Sta/Elev= 30
9799.093179.95639812.926179.33939843.785176.90669847.275 177.2139854.255178.9107
9857.745179.25229861.235178.97339875.199176.09959893.139170.74929900.306169.2918
9921.367166.47989945.453162.59499967.404 162.3899976.042161.9014    9999156.0111
   10001156.130510004.65158.375110008.61161.500610012.43163.583310016.96165.2356
10020.73165.9936 10038.4168.253410046.42168.738210068.16171.916910099.31175.1256
10106.13175.5922 10116.3175.589510139.74179.707910166.52182.688510200.89185.8816
#Mann= 3 , 0 , 0
9799.093    0.12       09799.093    0.12       010200.89    0.12       0
#XS Ineff= 2 , 0
       0                               0
Bank Sta=9799.093,10200.89
Exp/Cntr=0.3,0.1

Type RM Length L Ch R = 1 ,1009.328,93.125700,93.125700,93.125700
XS GIS Cut Line= 6
1219734.86939176624247.1199555981219734.72191648624169.248327623
1219728.12364638624137.0770930411219712.13926332624100.982721076
1219709.42135455624079.6215819161219736.80390495623922.611720775
#Sta/Elev= 30
9869.619171.51929881.798171.29489901.495171.47589934.318170.2738  9937.6169.8787
9957.492165.27359960.842 164.186 9967.54161.65339974.238159.98279977.587158.8819
9998.881151.3785   10001151.509910002.58151.811310019.86158.189810027.03160.5931
10036.95162.144110063.36168.150310073.34169.369210086.69171.287710120.07 175.121
10130.08175.835510136.75176.719710153.44176.881110160.71177.815310166.79178.8136
 10176.8179.728910183.48181.391310186.82181.787210196.51182.366610200.83182.8516
#Mann= 3 , 0 , 0
9869.619    0.12       09869.619    0.12       010200.83    0.12       0
#XS Ineff= 2 , 0
       0                               0
Bank Sta=9869.619,10200.83
Exp/Cntr=0.3,0.1

Type RM Length L Ch R = 1 ,916.2027,186.251300,186.251300,186.251300
XS GIS Cut Line= 6
1219789.75402672624235.9839426991219793.36966334 624151.82869052
1219798.72914558624122.3556867321219816.17191153624066.677590232
1219822.09633845624028.873840192 1219822.6261034623900.721217448
#Sta/Elev= 30
9861.908168.73869876.067168.95139885.915169.66839889.201169.58949915.494166.9773
9925.353 164.966  9938.5   163.79945.073162.54619951.726159.9677 9961.73155.0353
9965.064154.2356 9985.36152.14979995.687151.6158 9999.13151.874410002.58152.4965
10009.45154.326410019.75157.754810040.16 165.247 10046.8 166.89410070.05169.1052
10093.06172.045210112.76175.2079 10122.6175.431310132.45176.253710142.29177.3475
10152.14178.842710168.54179.990710181.67 182.09110188.23182.137310200.93183.8201
#Mann= 3 , 0 , 0
9861.908    0.12       09861.908    0.12       010200.93    0.12       0
#XS Ineff= 2 , 0
       0                               0
Bank Sta=9861.908,10200.93
Exp/Cntr=0.3,0.1

Type RM Length L Ch R = 1 ,729.9514,93.125700,93.125700,93.125700
XS GIS Cut Line= 6
1220048.08485838624250.2165283541220000.97678951624149.271698247
1219940.33118798624055.9874502341219924.78350487624026.745746423
1219905.58709167623968.2102347221219889.77702075623885.354950791
#Sta/Elev= 30
9799.031162.90669816.415163.52079832.813163.40239866.047164.59919895.378164.1196
9899.045163.70749906.378162.04879921.738160.54179940.937158.22519965.701153.5595
9995.773 149.01610000.05148.106810003.78147.918310007.74148.864210011.71150.4598
10015.66152.689910023.47158.447910027.19160.604210030.91162.168910038.34164.1836
10049.48 165.70210063.85168.4138 10070.9169.041710081.41170.382210115.55172.2778
10138.95174.832210148.97176.577610172.35 179.58610189.05 182.26810200.93183.1846
#Mann= 3 , 0 , 0
9799.031    0.12       09799.031    0.12       010200.93    0.12       0
#XS Ineff= 2 , 0
       0                               0
Bank Sta=9799.031,10200.93
Exp/Cntr=0.3,0.1

Type RM Length L Ch R = 1 ,636.8257,199.593800,199.593800,199.593800
XS GIS Cut Line= 6
1220556.27505782624490.4840772751220218.21769726624273.157589033
1220120.56362027624190.1446752851220061.45010611624105.194189578
1219970.21496174623887.512600824 1219810.3485873623688.788150266
#Sta/Elev= 30
9299.638175.92149311.405 175.5169334.807172.21319412.813 168.5469444.563163.7222
9490.819160.21229584.426161.8096 9614.44160.64839674.133161.32489689.734 160.334
9755.813161.51039839.944161.27899916.945162.79299935.338 160.6179963.224155.7287
9991.109148.148610001.56146.570910008.52147.382110057.27160.320110103.58169.1195
10126.28172.209810159.47174.940210174.72177.165210190.43180.8591   10226 187.134
10250.62189.647910275.03194.131610339.04196.324210388.02194.840910425.92197.0143
#Mann= 3 , 0 , 0
9299.638    0.12       09299.638    0.12       010425.92    0.12       0
#XS Ineff= 2 , 0
       09849.765                       0
Bank Sta=9299.638,10425.92
Exp/Cntr=0.3,0.1

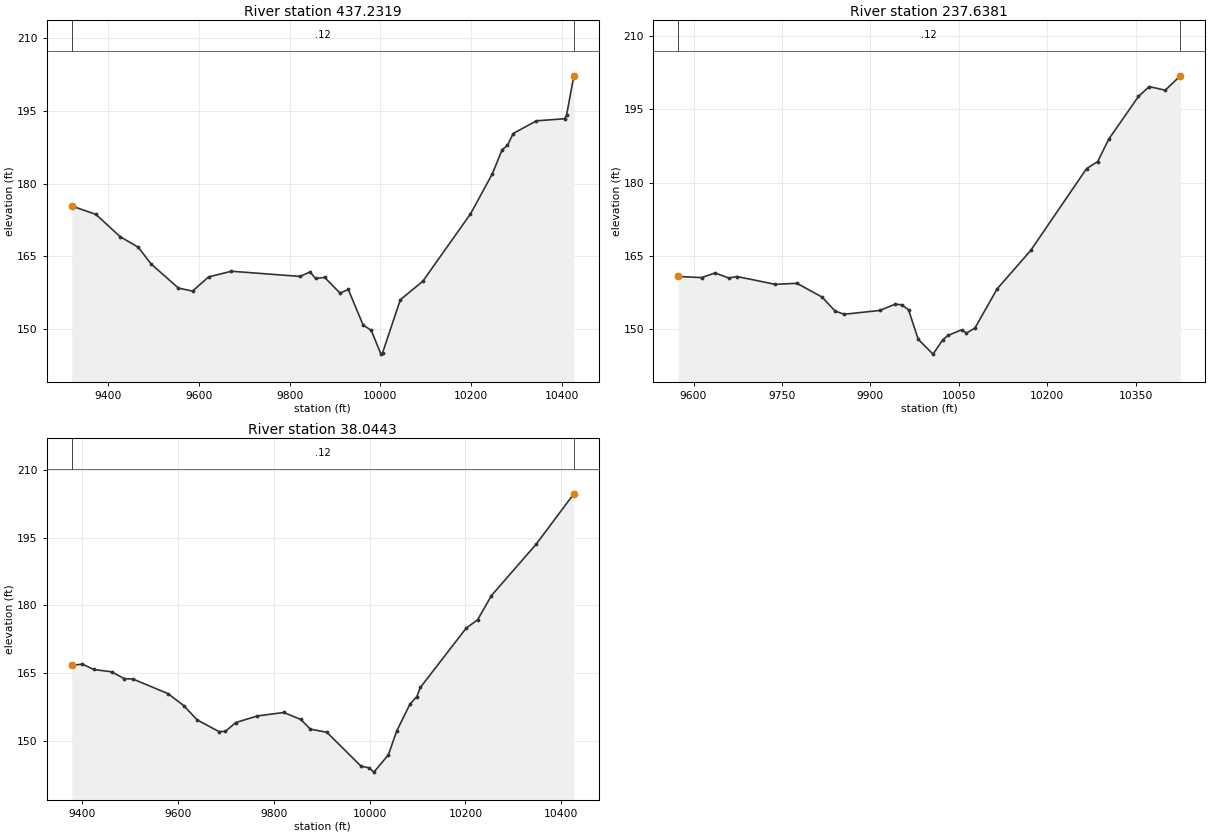
Type RM Length L Ch R = 1 ,437.2319,199.593800,199.593800,199.593800
XS GIS Cut Line= 6
1220658.02609479624473.8339075741220416.39895219624254.606755704
1220342.34382078624173.9157402811220256.45564249624042.870994776
1220144.00526327623811.8763845711219984.07866204623612.820331842
#Sta/Elev= 30
9320.227175.39069373.522173.66149426.728169.06549466.551166.89869495.084163.4372
 9555.15158.4715 9586.16157.8554  9621.6160.77519671.936161.94219823.083160.8741
9844.989161.80769857.071160.44829877.151160.68229910.947157.43979929.187158.1926
9961.903150.85659979.864149.748910001.11 144.85810004.65145.1209 10043.8156.0699
10093.26159.873810198.24173.751610246.43182.010510267.97186.985110279.83 187.896
10292.24190.328310343.63192.950110405.44 193.37710409.87 194.09510425.96202.2248
#Mann= 3 , 0 , 0
9320.227    0.12       09320.227    0.12       010425.96    0.12       0
#XS Ineff= 2 , 0
       09886.831                       0
Bank Sta=9320.227,10425.96
Exp/Cntr=0.3,0.1

Type RM Length L Ch R = 1 ,237.6381,199.593800,199.593800,199.593800
XS GIS Cut Line= 5
1220688.77662348624164.7399647651220389.54769379623862.941517157
1220388.18960979623861.4733183161220381.96534081623855.225122652
 1220081.7514734623567.002163379
#Sta/Elev= 30
9574.006160.7972 9613.74160.56829636.463161.51839659.941160.47799673.741160.7861
9738.482159.18629775.443159.39719818.194156.57549840.124153.72969855.472153.0679
9916.049 153.8479941.766155.11519953.327155.00949964.867153.95659981.285147.9263
10006.39144.914910022.95147.861710032.05148.749410054.79149.890110063.16149.2246
10077.53150.258510115.27158.279610172.12166.121410266.87182.844310285.81184.2909
10304.76188.914210354.96197.606610373.15199.627410400.44198.889610425.99201.8263
#Mann= 3 , 0 , 0
9574.006    0.12       09574.006    0.12       010425.99    0.12       0
#XS Ineff= 2 , 0
       09941.096                       0
Bank Sta=9574.006,10425.99
Exp/Cntr=0.3,0.1

Type RM Length L Ch R = 1 , 38.0443,0.000000,0.000000,0.000000
XS GIS Cut Line= 6
1220955.87913021624066.8297597471220611.88747418623746.269749433
 1220543.6908727623709.8756099191220415.66016173623678.730851442
 1220343.6449798623646.2259267271220115.90350413623471.406462461
#Sta/Elev= 30
9379.259166.72859401.566166.97389425.012165.79119462.526165.27499488.623163.7744
9506.991163.67159579.755160.44729612.579157.80719640.714154.6269 9685.94152.0476
9699.504152.0838 9721.16154.04839766.395155.50749821.362156.27079856.672154.7276
9876.538152.58989911.085  151.889982.272144.39189998.972144.020310009.08143.0612
10039.38146.907810056.39 152.09910084.44158.154310098.68159.7941 10106.1161.8348
10201.52174.952810225.28 176.80410254.23 182.17410347.24193.526810425.93204.6961
#Mann= 3 , 0 , 0
9379.259    0.12       09379.259    0.12       010425.93    0.12       0
#XS Ineff= 2 , 0
       09780.939                       0
Bank Sta=9379.259,10425.93
Exp/Cntr=0.3,0.1